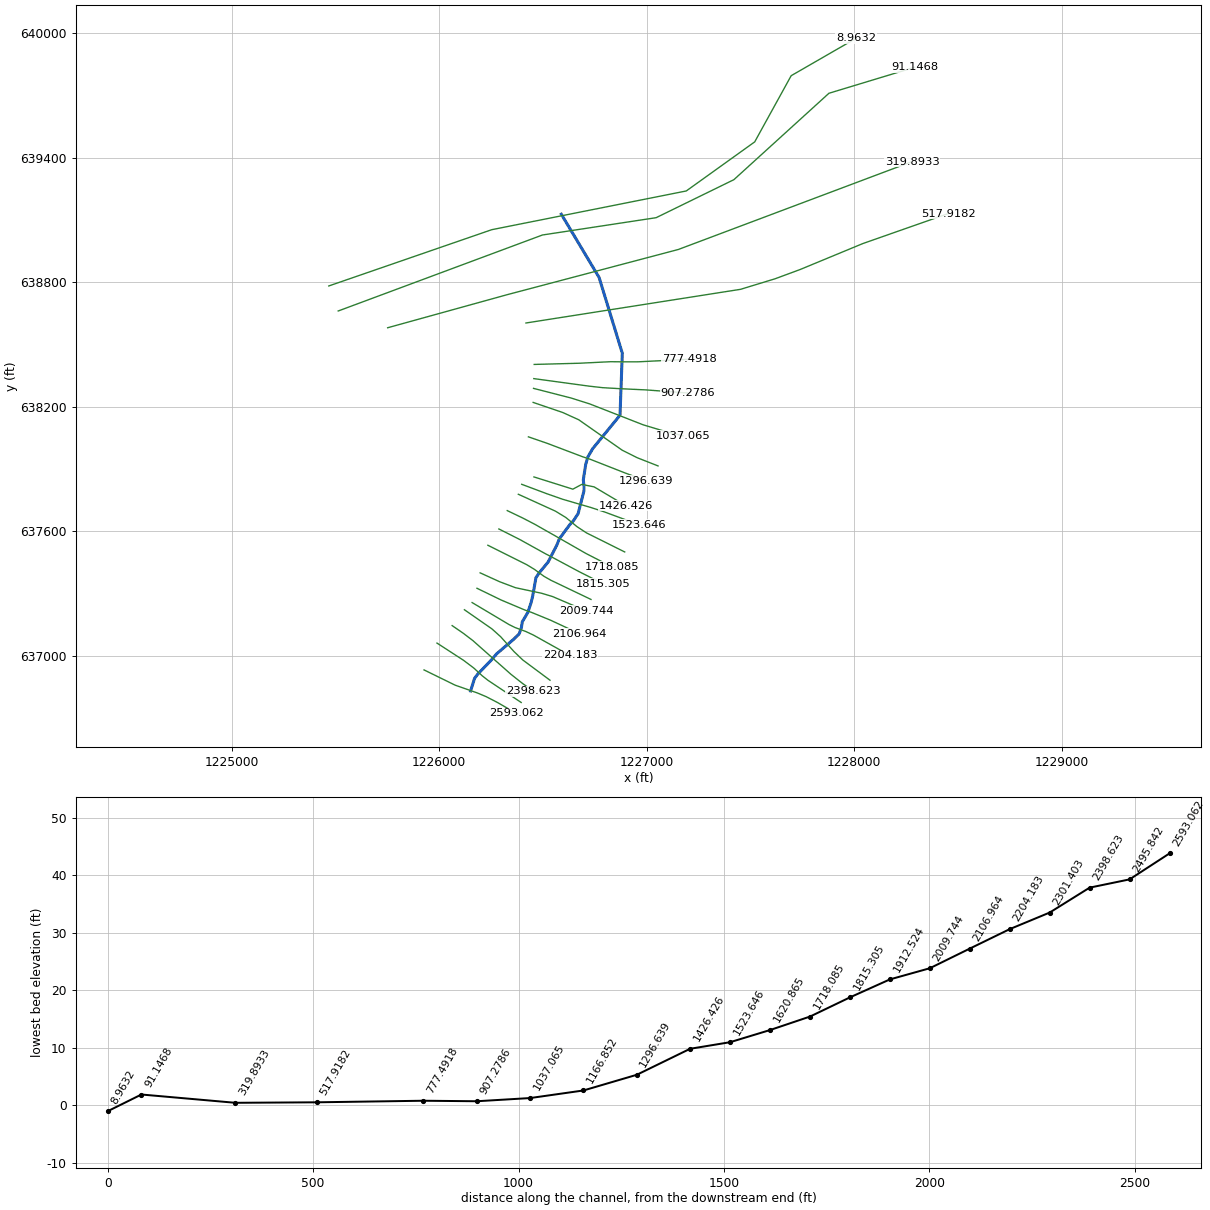
--- 579_ras.prj (project) ---

Proj Title=579
Current Plan=p01
Default Exp/Contr=0.3,0.1
English Units
Geom File=g01
Flow File=f01
Plan File=p01
Y Axis Title=Elevation
X Axis Title(PF)=Main Channel Distance
X Axis Title(XS)=Station
BEGIN DESCRIPTION:
RFD model 579 exported to HEC-RAS
END DESCRIPTION:

--- 579_ras.p01 (plan) ---

Plan Title=Plan 01
Program Version=4.10
Short Identifier=Plan 01
Geom File=g01
Flow File=f01
Subcritical Flow
Calc Critical at every XS
Secant Critical Depth

--- 579_ras.f01 (steady flow) ---

Flow Title=Flow 01
Program Version=5.01
Number of Profiles= 5
Profile Names=10yr,25yr,50yr,100yr,500yr
River Rch & RM=579,22,2593.062
  441.29  537.25  643.47  700.64  843.62
River Rch & RM=579,22,2495.842
  444.83  542.21  649.58  708.13  853.93
River Rch & RM=579,22,2398.623
  449.73  549.05  658.01  718.49  868.23
River Rch & RM=579,22,2301.403
  476.26  586.33  704.03  775.29   947.1
River Rch & RM=579,22,2106.964
  480.05  591.68  710.64  783.48  958.55
River Rch & RM=579,22,2009.744
  483.17  596.09   716.1  790.25  968.02
River Rch & RM=579,22,1912.524
  496.56  615.06  739.55  819.44 1008.99
River Rch & RM=579,22,1815.305
  500.11  620.11   745.8  827.23 1019.97
River Rch & RM=579,22,1718.085
  504.21  625.94  753.01  836.25 1032.68
River Rch & RM=579,22,1620.865
  515.09  641.44  772.21  860.28 1066.67
River Rch & RM=579,22,1523.646
  523.98  654.15  787.96  880.05 1094.73
River Rch & RM=579,22,1426.426
  528.35   660.4   795.7  889.79 1108.59
River Rch & RM=579,22,1296.639
  531.04  664.27   800.5  895.82 1117.19
River Rch & RM=579,22,1166.852
  533.19  667.34  804.31  900.63 1124.04
River Rch & RM=579,22,1037.065
  559.44  705.13  851.21  959.94 1209.04
River Rch & RM=579,22,907.2786
  560.43  706.56  852.99   962.2 1212.29
River Rch & RM=579,22,777.4918
  564.86  712.96  860.94   972.3 1226.85
River Rch & RM=579,22,517.9182
  575.94  729.02  880.89   997.7 1263.54
River Rch & RM=579,22,319.8933
  583.92  740.61  895.31  1016.1 1290.21
River Rch & RM=579,22, 91.1468
  586.24  743.98   899.5 1021.46 1297.99
River Rch & RM=579,22,  8.9632
  587.16  745.32  901.17 1023.59 1301.09
Boundary for River Rch & Prof#=579,22,1
Up Type= 0
Dn Type= 2
Boundary for River Rch & Prof#=579,22,2
Up Type= 0
Dn Type= 2
Boundary for River Rch & Prof#=579,22,2
Up Type= 0
Dn Type= 2
Boundary for River Rch & Prof#=579,22,2
Up Type= 0
Dn Type= 2
Boundary for River Rch & Prof#=579,22,2
Up Type= 0
Dn Type= 2

--- 579_ras.g01 (geometry) ---

Geom Title=579
Program Version=4.10

River Reach=579,22
Reach XY= 30
1226151.21721569636829.298292324 1226170.3838785636890.131607056
1226185.38387462636910.1316006631226252.05052367636979.298244879
1226277.05051711637008.4649021631226357.88382861637077.631545946
1226385.38382128637104.2982039151226396.21715233637135.131527752
1226400.38381857637162.6315195111226427.05047864 637207.63150534
 1226442.8838087637255.1314908121226450.38380742637285.964814782
1226466.21713868637375.1314545121226480.38380173 637396.79811433
1226524.55045694637450.1314305371226566.21711367637530.964738682
1226579.55044401637563.4647286981226628.71709812637630.131374136
1226647.88375971637650.9647006991226669.55042097637684.298023507
1226697.88374916637794.2979900841226697.88374984637817.631316498
1226694.55041835637846.7979745861226706.21708372637921.797951981
1226716.21708182637956.7979413121226739.55040941637996.797928765
1226871.49481964638158.4645436261226882.45552832638457.231107309
1226770.63347581638822.3643400821226588.50882009639127.214264333

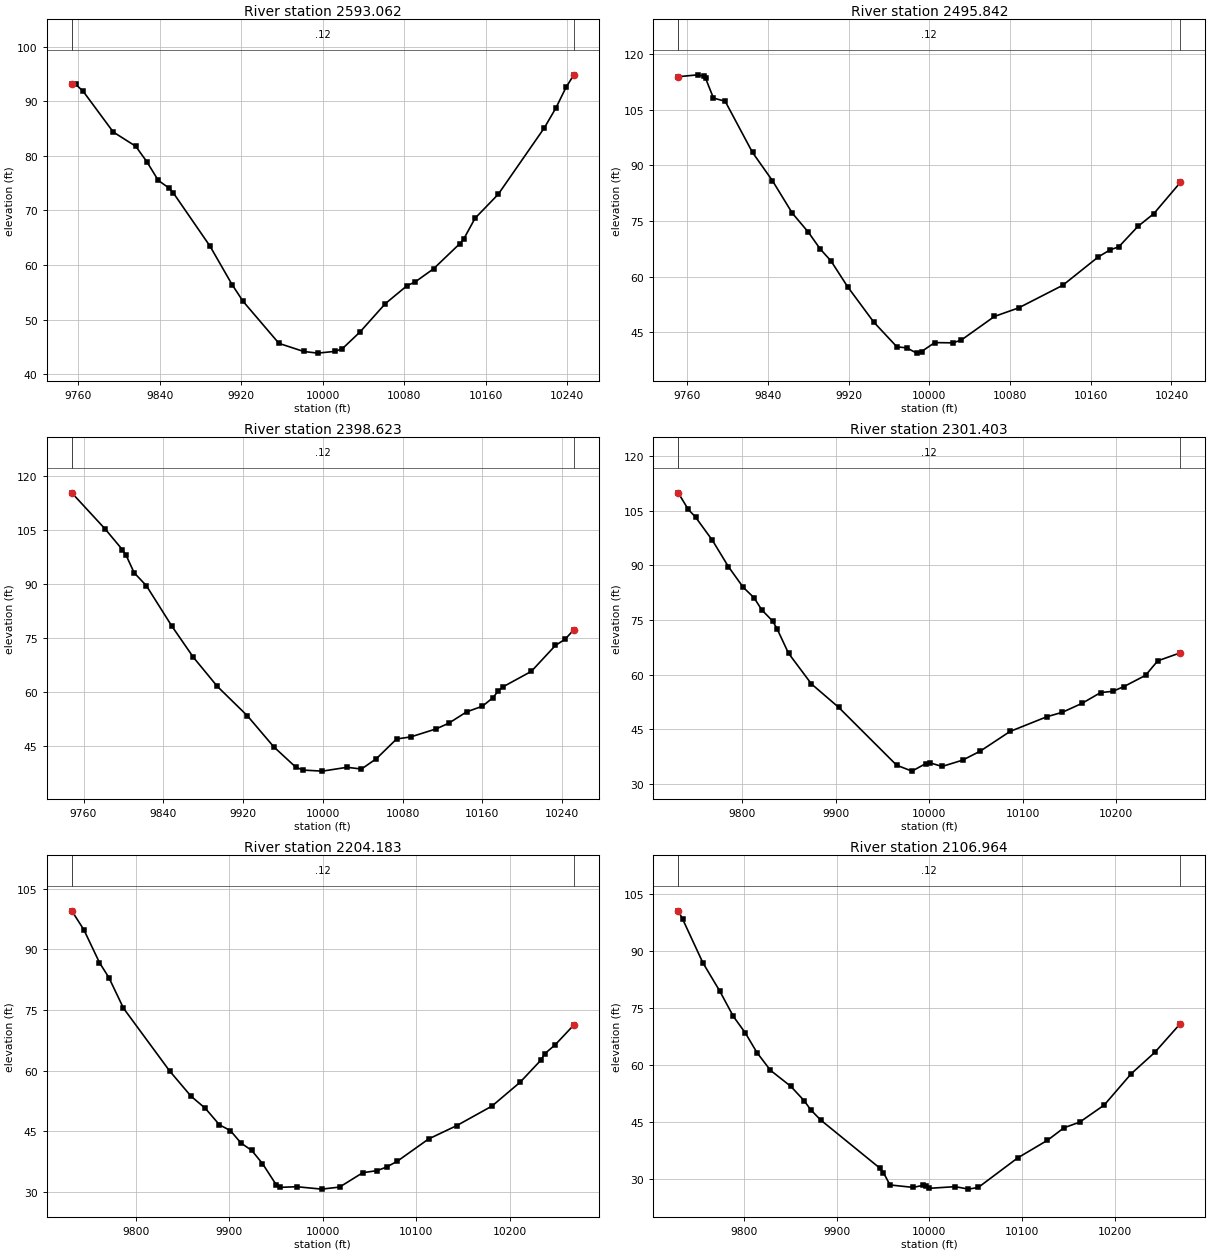
Type RM Length L Ch R = 1 ,2593.062,97.219700,97.219700,97.219700
XS GIS Cut Line= 6
1225926.77977202636930.7863233891226076.44450549636857.361137753
1226184.26884402636819.5170041561226226.16478766636801.853321638
 1226280.3371222636773.9761756251226371.92218979 636721.24375645
#Sta/Elev= 30
9753.42993.236079757.29893.115659764.66991.821419794.15284.373389816.26481.75758
 9827.3278.882839838.37675.504089849.365 74.03979852.98373.259629889.16463.46007
9910.87356.401829921.68653.329489956.92545.622559981.24144.13858 9995.0343.83569
10012.2744.1643610019.1844.6465210036.5147.7070510061.4352.91139 10082.956.22831
10090.2756.8323410108.7259.2886510134.5563.9015510138.2464.6920410149.5368.56451
10172.2572.9475310217.6785.1614510229.0388.8106210238.8792.5533510246.5694.85578
#Mann= 3 , 0 , 0
9753.429    0.12       09753.429    0.12       010246.56    0.12       0
#XS Ineff= 2 , 0
       0                               0
Bank Sta=9753.429,10246.56
Exp/Cntr=0.3,0.1

Type RM Length L Ch R = 1 ,2495.842,97.219600,97.219600,97.219600
XS GIS Cut Line= 6
1225989.22346577637060.0988396451226116.94974202636977.220760876
1226166.48802661636939.9346311641226207.94530602636901.892318632
1226233.95340751636881.3605853341226395.15476029 636773.72541381
#Sta/Elev= 30
9751.239113.9795 9770.66114.48919776.668114.12359778.402113.50619786.144108.2101
9797.757107.34639824.85493.515699844.52385.922919864.30277.113569880.12572.00103
9891.99267.423419902.65164.19974 9919.0857.254559944.93547.717229967.90841.02033
  9977.740.738379987.49239.317879992.38839.7532310005.4142.1631410023.26 42.0927
10031.6242.8238610064.5949.2282410088.5251.5333410132.32 57.645810167.5965.32745
10179.3567.2328110187.7868.0222710206.7973.5595410222.4776.9742910248.7885.40945
#Mann= 3 , 0 , 0
9751.239    0.12       09751.239    0.12       010248.78    0.12       0
#XS Ineff= 2 , 0
       0                               0
Bank Sta=9751.239,10248.78
Exp/Cntr=0.3,0.1

Type RM Length L Ch R = 1 ,2398.623,97.219700,97.219700,97.219700
XS GIS Cut Line= 6
1226062.38917717637144.2314981461226115.64693848637107.642703695
1226162.55388836637071.8189327321226345.82323504636909.550244798
1226400.13138617636866.542901814 1226453.8156393636828.283266756
#Sta/Elev= 30
 9748.18115.31759781.537105.28869798.91999.513419802.77797.884139810.73893.08005
9823.04689.459129848.49878.259429870.11969.569659894.10561.479029924.29353.29065
9950.72644.663429972.75439.013079979.973 38.17299999.65337.8805310024.2838.94518
10038.7838.4648810053.7941.3592610074.01 46.821110088.2247.4022910113.6449.63066
10126.3551.2143610144.2454.3664910160.0955.9459910170.6658.3056910175.9460.18264
10180.7561.3320910209.1565.6372810233.32 72.849710243.0974.5920810251.8177.22729
#Mann= 3 , 0 , 0
 9748.18    0.12       0 9748.18    0.12       010251.81    0.12       0
#XS Ineff= 2 , 0
       0                               0
Bank Sta=9748.18,10251.81
Exp/Cntr=0.3,0.1

Type RM Length L Ch R = 1 ,2301.403,97.219700,97.219700,97.219700
XS GIS Cut Line= 6
1226121.43352376637220.7557745831226254.55201747637128.136785717
1226296.19672924637090.6181768161226360.08395953 637019.53595688
1226402.99346713636978.5112663091226534.04482436636881.036699857
#Sta/Elev= 30
9731.675109.9452 9742.32105.41759750.148103.2861 9768.2696.883289785.37789.64968
9801.03484.040199812.77781.110989820.94877.821789832.58674.740659837.29672.62904
9849.55765.902729874.07957.473859902.99851.091859965.10435.178749981.48333.54893
9996.13535.5991410001.0835.8056610013.6834.8275110035.6636.5641310054.5339.04431
 10086.344.43487 10125.5 48.4603 10142.349.70835 10163.352.1619610183.21 55.1171
10196.2355.4594610208.1856.7766810231.1759.8415210244.1863.8200710268.3366.02649
#Mann= 3 , 0 , 0
9731.675    0.12       09731.675    0.12       010268.33    0.12       0
#XS Ineff= 2 , 0
       0                               0
Bank Sta=9731.675,10268.33
Exp/Cntr=0.3,0.1

Type RM Length L Ch R = 1 ,2204.183,97.219700,97.219700,97.219700
XS GIS Cut Line= 6
1226158.60121854637255.3276074131226337.37519129 637148.91667862
1226365.76000987637134.9322558121226417.17554459637115.946751127
1226452.81853383637099.3588556561226630.03370281637000.515633085
#Sta/Elev= 30
9731.63799.519969744.58394.829439761.26886.698969771.30983.005589786.926 75.4231
9836.21659.911869859.124 53.65349874.39650.660179889.55746.567369901.12245.16189
9912.57642.060149924.03140.239479935.48536.994139950.29131.708149953.94831.10549
9972.196  31.2599998.853 30.667810017.9331.17519 10042.7 34.7286 10058.335.25511
10068.13 36.1361 10079.437.5335310113.2143.0904610143.2646.3904310180.8351.21248
10210.8857.1015910233.4262.6410410237.1864.1516210248.4566.3781710268.3771.28172
#Mann= 3 , 0 , 0
9731.637    0.12       09731.637    0.12       010268.37    0.12       0
#XS Ineff= 2 , 0
       0                               0
Bank Sta=9731.637,10268.37
Exp/Cntr=0.3,0.1

Type RM Length L Ch R = 1 ,2106.964,97.219600,97.219600,97.219600
XS GIS Cut Line= 6
1226181.92417065 637324.248119671226298.74347383 637267.57383137
1226413.26243096637219.2954617691226447.59001556637206.910024273
1226536.70754056637170.3628174591226676.72513339637104.964130591
#Sta/Elev= 30
9729.261100.6815 9733.9798.513389755.81486.988889774.04779.520919788.63372.86571
9801.61768.475069814.15963.299939828.74558.612559850.62454.403569865.06650.60481
9872.18748.195749882.86945.515499946.53232.854289950.51731.650149957.63828.38612
9982.562 27.73799993.06128.269889996.55628.1759710000.03 27.497410028.0627.93604
10042.2427.2826810052.8827.7305710095.4335.52618 10127.540.1674110145.4743.48605
10162.1344.9322710188.6649.45221 10217.8 57.716510243.3163.3674710270.7570.92476
#Mann= 3 , 0 , 0
9729.261    0.12       09729.261    0.12       010270.75    0.12       0
#XS Ineff= 2 , 0
       0                               0
Bank Sta=9729.261,10270.75
Exp/Cntr=0.3,0.1

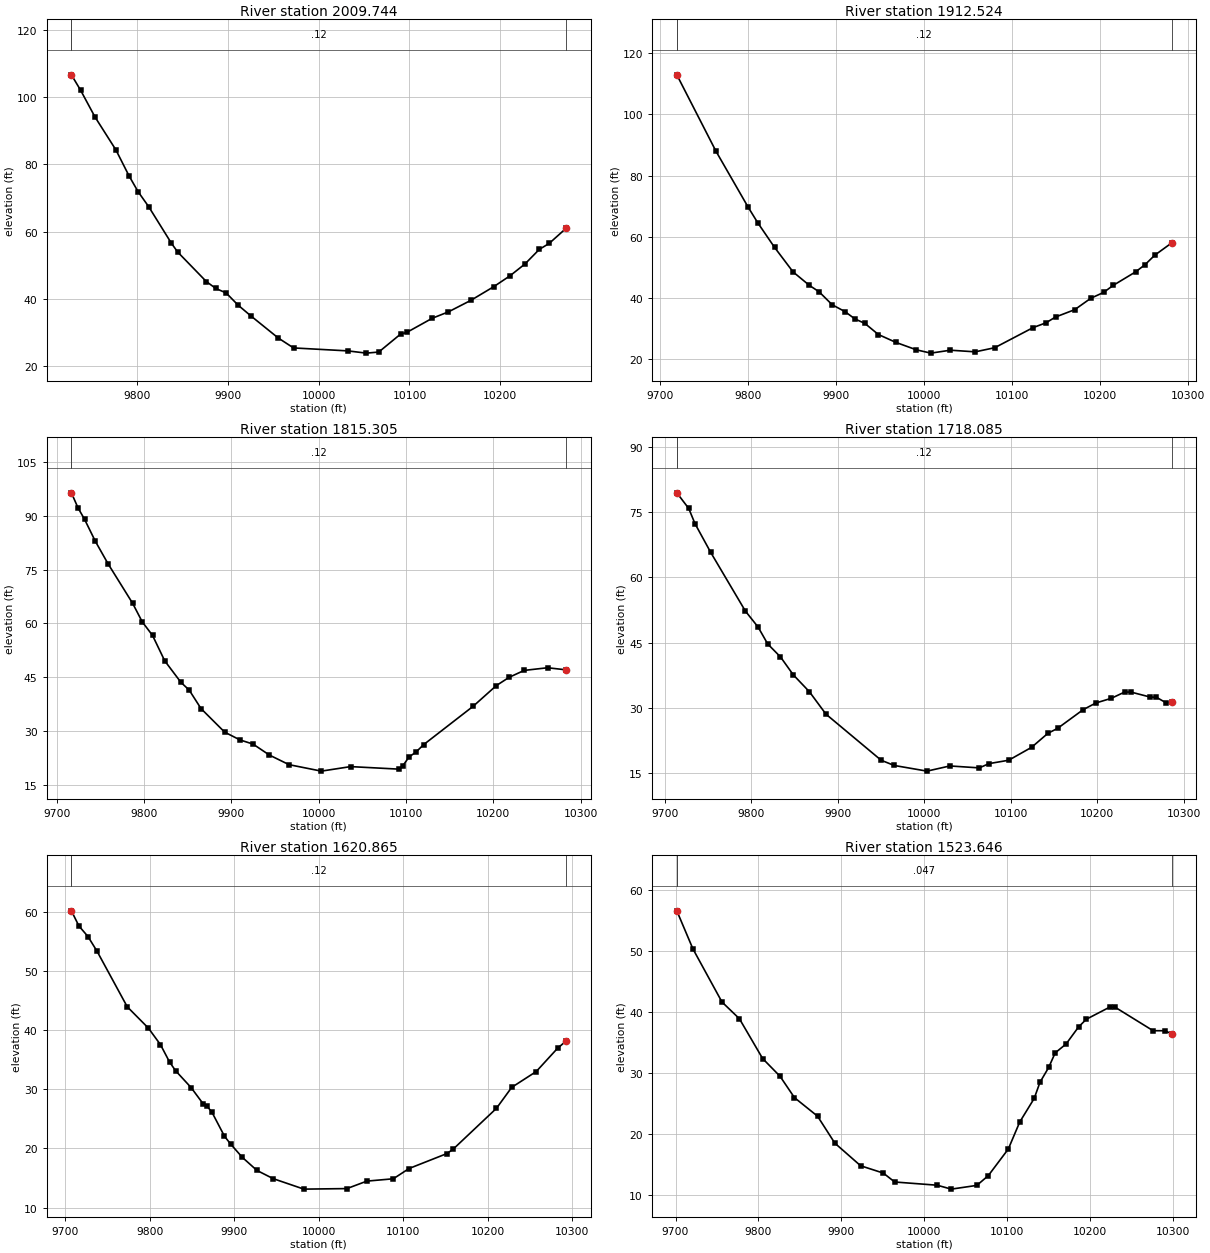
Type RM Length L Ch R = 1 ,2009.744,97.219700,97.219700,97.219700
XS GIS Cut Line= 6
1226197.25955542637398.5736919751226290.47098009637356.122218731
1226367.54354618 637327.001128111226493.91969405637300.123172253
1226546.51095033637284.2838581881226708.47966278637214.962620277
#Sta/Elev= 30
9727.348106.67629737.488102.09469753.31994.145569776.40484.331739790.825 76.6376
9800.81471.918919812.455  67.4759837.47656.60782 9844.4953.944489876.05545.17021
9886.57743.100979897.91941.772519911.12738.137429924.75435.033499955.34128.36914
9972.18925.4139910032.1224.5315210052.4223.8668210066.1224.1882610090.1129.51848
10096.9830.0285910125.1934.2566610142.8336.1359810167.5239.5524410192.7243.61392
10210.71 46.859110227.2950.39689 10243.154.74096 10253.956.4934910272.6661.02407
#Mann= 3 , 0 , 0
9727.348    0.12       09727.348    0.12       010272.66    0.12       0
#XS Ineff= 2 , 0
       0                               0
Bank Sta=9727.348,10272.66
Exp/Cntr=0.3,0.1

Type RM Length L Ch R = 1 ,1912.524,97.219700,97.219700,97.219700
XS GIS Cut Line= 6
1226234.71455652637531.4968155651226421.30493949637438.243386658
1226458.88102915637415.498708534 1226505.1200214637381.798629719
1226537.72864932637363.1601824421226731.54979613 637270.42207462
#Sta/Elev= 30
9718.904112.93149763.38187.956349799.89469.681619810.80864.578189829.90156.52845
9851.01148.480299869.50744.088129880.605 41.97419895.40337.75353  9910.235.46194
9921.298  33.1069932.57531.646659947.91528.012819967.89325.432679991.22322.99323
10007.5521.9242410029.7822.8819910058.03 22.344510080.1623.6957310123.8130.27841
10138.36 31.831810149.2733.7351710171.0936.1418610189.2739.8556510203.8241.76961
10214.7344.0705310240.1948.48729 10251.150.8816610262.0253.9559410281.0957.93101
#Mann= 3 , 0 , 0
9718.904    0.12       09718.904    0.12       010281.09    0.12       0
#XS Ineff= 2 , 0
       0                               0
Bank Sta=9718.904,10281.09
Exp/Cntr=0.3,0.1

Type RM Length L Ch R = 1 ,1815.305,97.219700,97.219700,97.219700
XS GIS Cut Line= 6
 1226287.5597123637610.1360045071226388.49771273637559.188613818
1226512.31407395637490.4783384151226538.71882371637476.930601167
 1226673.8136445637404.573611398 1226789.1066149637346.494763282
#Sta/Elev= 30
9716.65296.41896 9724.3192.17862 9731.6689.062089744.06782.907039758.62976.62805
9786.786 65.60529797.81260.430379809.59756.645929823.53749.565199842.16843.54249
9851.60241.398519865.12436.24184 9892.1729.679159909.70727.505159924.71626.34289
9943.47623.274989965.989 20.598110002.97  18.79910036.4720.06071 10092.319.34695
10096.0220.1828610103.46 22.779210110.9124.0210310120.27 26.214710176.9336.90492
10203.3142.64268   1021844.9555410235.2746.8900310262.0947.6312810283.3547.04883
#Mann= 3 , 0 , 0
9716.652    0.12       09716.652    0.12       010283.35    0.12       0
#XS Ineff= 2 , 0
       0                               0
Bank Sta=9716.652,10283.35
Exp/Cntr=0.3,0.1

Type RM Length L Ch R = 1 ,1718.085,97.219600,97.219600,97.219600
XS GIS Cut Line= 6
1226327.92420493637698.6120252131226403.19715905637662.553032499
1226459.87360199637633.1202399591226579.55289568637565.212024667
1226707.93769721637491.6483132691226831.57858654637428.249799929
#Sta/Elev= 30
9714.06979.383529727.82475.796479735.09972.291779753.289 65.68439793.30552.22898
9808.024 48.54619819.11444.674499833.90241.688029848.68937.579459867.291 33.6995
9886.46628.545249950.27917.957369965.36816.7617410003.2115.4613110029.6616.64949
10063.6716.20616   1007517.1892410097.6717.9645610124.1220.9278610143.0224.15151
10154.17 25.280410183.6729.5685610198.4231.1109210216.3632.19377 10231.633.61612
10238.9833.61897 10261.132.4798610268.4732.4226510279.5331.1543610285.9231.30177
#Mann= 3 , 0 , 0
9714.069    0.12       09714.069    0.12       010285.92    0.12       0
#XS Ineff= 2 , 0
       0                               0
Bank Sta=9714.069,10285.92
Exp/Cntr=0.3,0.1

Type RM Length L Ch R = 1 ,1620.865,97.219700,97.219700,97.219700
XS GIS Cut Line= 6
1226381.39038663 637777.388200771226559.93606076637696.110611377
1226610.05370967637665.584987748 1226663.5638319637621.640665639
1226709.76368364637591.212898768 1226894.0409138637499.329453452
#Sta/Elev= 30
9707.275 60.12059716.15857.565289726.88455.776729737.61153.296629773.36743.91444
9798.39540.310119812.69837.514489823.424 34.58759830.59333.111649848.87930.27728
9863.50827.465019867.16527.232959873.58326.111889888.43422.049629895.85920.70391
9909.62518.472119926.797 16.28169946.00514.890519982.39113.1187510033.3113.20897
10056.9114.4718610088.2314.8661310106.8316.5991510151.4819.1140310158.9219.85095
10210.2326.7597110228.35 30.307610257.3332.97546 10282.736.9265110292.7438.13631
#Mann= 3 , 0 , 0
9707.275    0.12       09707.275    0.12       010292.74    0.12       0
#XS Ineff= 2 , 0
       0                               0
Bank Sta=9707.275,10292.74
Exp/Cntr=0.3,0.1

Type RM Length L Ch R = 1 ,1523.646,97.219700,97.219700,97.219700
XS GIS Cut Line= 6
1226397.59648835637825.3797025891226517.58688682637780.408896355
1226595.36801039637753.1646796571226731.58911232637713.393746401
1226796.06209568637692.364643527 1226961.6054605637631.011243169
#Sta/Elev= 30
9701.58856.647919721.01450.404859756.05141.696719777.07338.953129805.10332.42509
9826.12529.508919843.53526.006289871.34522.968349892.20218.546689923.31614.83764
9950.70313.637229964.39712.1763810015.6811.6464710032.72 11.005810063.5211.61815
10077.3313.2179210101.4817.5847310115.2922.0186310132.6925.8750610139.6928.53058
10150.1830.9547310158.0233.3497610171.1834.8094610186.3437.6222210195.6738.87254
10223.6640.8431810230.6640.8120410276.1436.9876310290.1436.9826910298.4236.50561
#Mann= 3 , 0 , 0
9701.588   0.047       09701.588   0.047       010298.42   0.047       0
#XS Ineff= 2 , 0
       0                               0
Bank Sta=9701.588,10298.42
Exp/Cntr=0.3,0.1

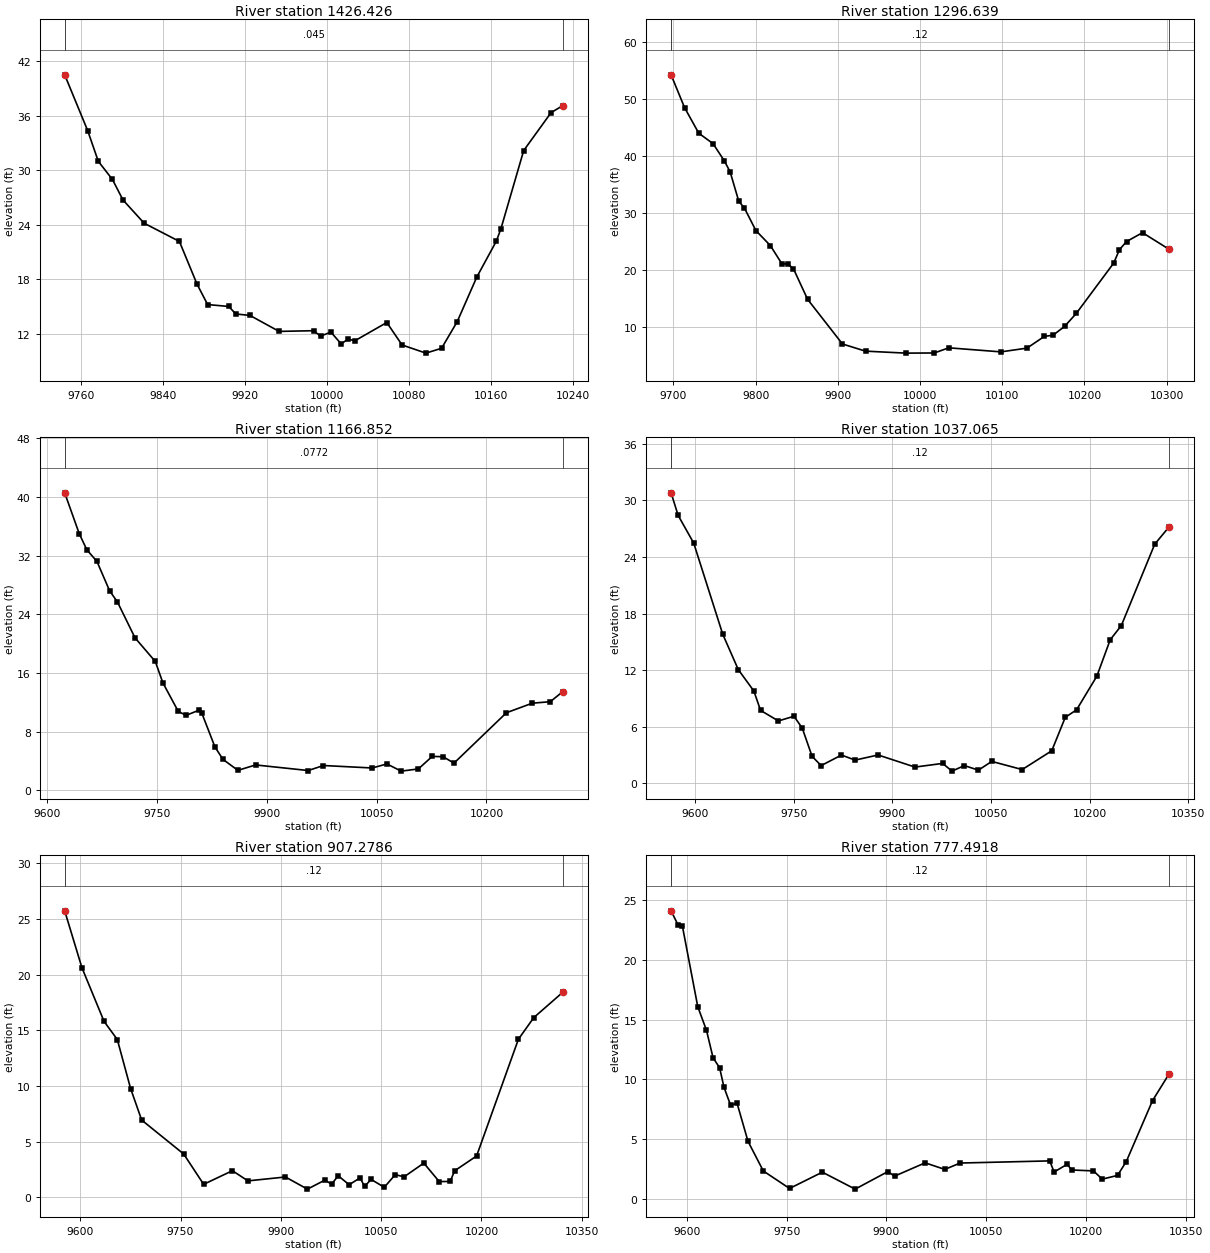
Type RM Length L Ch R = 1 ,1426.426,129.786800,129.786800,129.786800
XS GIS Cut Line= 5
1226456.69221139637860.9259943521226644.22571367637801.911955193
1226686.84696421637824.8618593071226746.51671496637813.059051499
1226901.26463988637721.259434968
#Sta/Elev= 30
9744.344 40.50119766.811 34.3449 9777.1330.976559790.88728.985169801.20626.72375
9821.84324.163839856.23722.159389873.43417.455959883.75315.209589904.38914.99678
9911.268 14.17279925.02614.014169953.50812.252749987.04412.33006 9993.9711.73417
   1000412.1750510014.0410.8796710020.7211.4010510027.4111.2220510058.54 13.2315
10073.4310.7594110096.699.86106210111.9510.3944510127.2113.3216610146.2818.22698
10165.3622.1839610169.8923.5663610192.0632.1631610218.7636.33637 10230.1 37.1058
#Mann= 3 , 0 , 0
9744.344   0.045       09744.344   0.045       0 10230.1   0.045       0
#XS Ineff= 2 , 0
       0                               0
Bank Sta=9744.344,10230.1
Exp/Cntr=0.3,0.1

Type RM Length L Ch R = 1 ,1296.639,129.786800,129.786800,129.786800
XS GIS Cut Line= 6
1226429.87475686638054.1742754761226521.80045128 638022.42476959
1226691.78420782637957.9881922861226730.14592788637945.108832855
1226894.63558463637880.521498326 1226997.2512033637842.138557649
#Sta/Elev= 30
9697.11154.194639713.44648.455369730.80143.940789748.156 42.1175 9762.0439.05435
9768.98237.143519779.395 32.01979786.33730.799099800.28526.852929817.82824.22524
9831.86321.03073 9838.8820.997619845.89720.169249863.14614.789759905.5446.944783
9933.6135.6868279982.6545.33913910017.275.36590810034.89 6.2711710098.335.559776
10130.066.218399 10151.28.28197410161.788.48396310175.8810.0473110189.9812.30383
10235.53 21.147610242.5423.51543 10251.224.9302310270.5626.4841510302.8923.56802
#Mann= 3 , 0 , 0
9697.111    0.12       09697.111    0.12       010302.89    0.12       0
#XS Ineff= 2 , 0
       0                               0
Bank Sta=9697.111,10302.89
Exp/Cntr=0.3,0.1

Type RM Length L Ch R = 1 ,1166.852,129.786800,129.786800,129.786800
XS GIS Cut Line= 6
1226452.77685666638220.0796008371226594.80360298638171.709367026
1226672.54716671638136.4484336671226882.07902644637989.732715946
1226954.82417893637953.2886515271227054.89564674 637913.93936621
#Sta/Elev= 30
9623.67840.582769643.52235.01724 9653.9232.812549667.78431.215899685.11327.20502
9695.79625.689059719.77220.797669747.49917.572769757.89714.651689778.81610.77166
9789.47310.220069807.23410.925519810.78610.597989828.9765.9153589839.9244.217547
9860.3462.7191259884.5953.4555879956.4852.6938539977.239 3.3780610043.893.040847
10064.023.59353210083.442.61209310106.942.90914110125.984.62509110140.884.572079
10155.663.70184710227.3310.5792710262.6311.8800810287.2712.0847310304.1913.44899
#Mann= 3 , 0 , 0
9623.678  0.0772       09623.678  0.0772       010304.19  0.0772       0
#XS Ineff= 2 , 0
       0                               0
Bank Sta=9623.678,10304.19
Exp/Cntr=0.3,0.1

Type RM Length L Ch R = 1 ,1037.065,129.786900,129.786900,129.786900
XS GIS Cut Line= 6
1226454.62585963638287.7531095791226636.28724812638241.128955414
1226725.83855812638212.7393302721226983.19322788638112.078149229
 1227072.4185765 638085.181577671227175.13103453638059.186041834
#Sta/Elev= 30
9563.64830.792489574.35828.399529598.06825.461679642.10215.822349665.81212.05657
9689.5229.7838049699.6837.7355879726.781 6.611889750.4917.1106679763.0565.860582
9778.0142.8653759791.7811.8792169822.7562.9979899843.4072.4624739878.4363.005501
9934.5351.7227659976.6092.1110159990.8271.293363 10009.51.88141210031.021.398478
10051.272.32247110097.561.45909310142.513.45225810163.076.997346 10180.27.789057
10211.0411.3542810231.3915.2180210248.3116.7253610299.0825.34906 10320.927.18203
#Mann= 3 , 0 , 0
9563.648    0.12       09563.648    0.12       0 10320.9    0.12       0
#XS Ineff= 2 , 0
       0                               0
Bank Sta=9563.648,10320.9
Exp/Cntr=0.3,0.1

Type RM Length L Ch R = 1 ,907.2786,129.786800,129.786800,129.786800
XS GIS Cut Line= 6
1226455.91154439638334.8091714761226721.86041484638298.620389547
1226788.46013955638291.1047853181226875.17614392638286.086232808
1226995.70019581638280.4419912491227197.07265698638265.542693106
#Sta/Elev= 30
9576.71725.732479602.44520.632159635.55515.808239655.42214.173819675.2889.774874
9691.8436.9415859754.754 3.889819784.5531.1691539827.5972.3926479850.7591.478728
9906.8871.8276879939.7740.7377139966.065 1.550899975.9241.1774949985.7831.939381
10002.211.13225310018.631.753986 10025.20.97842210035.061.60998310054.760.902293
10071.192.03874310084.321.83989410113.883.074829 10136.91.41559310153.35 1.42698
10159.932.38190110192.833.71542710255.3414.1983810278.3616.1431410321.5818.40898
#Mann= 3 , 0 , 0
9576.717    0.12       09576.717    0.12       010321.58    0.12       0
#XS Ineff= 2 , 0
       0                               0
Bank Sta=9576.717,10321.58
Exp/Cntr=0.3,0.1

Type RM Length L Ch R = 1 ,777.4918,259.573600,259.573600,259.573600
XS GIS Cut Line= 6
1226457.77925294638403.1673043311226675.29233679638408.910017777
1226826.00699457638416.2970208241226881.93302633638415.712471288
1226957.87258545638415.7577072971227205.01497468  638428.0579378
#Sta/Elev= 30
9576.58624.108439587.09122.921469593.65522.804269616.62916.092919629.75714.10643
9639.60311.817729649.44910.980459656.0139.3489599665.8597.8608519675.7058.000977
9692.114 4.821769715.0882.3450299754.4720.882368 9803.712.2457169852.9810.826869
9902.2532.2980119912.1071.9100459958.0793.0271989987.6082.47686110010.583.009048
10145.173.18861910151.742.25786810171.452.91037610178.022.42804310210.872.351551
10224.011.66166210247.011.97430310260.153.13635110299.568.23283210324.3910.46293
#Mann= 3 , 0 , 0
9576.586    0.12       09576.586    0.12       010324.39    0.12       0
#XS Ineff= 2 , 0
       0                               0
Bank Sta=9576.586,10324.39
Exp/Cntr=0.3,0.1

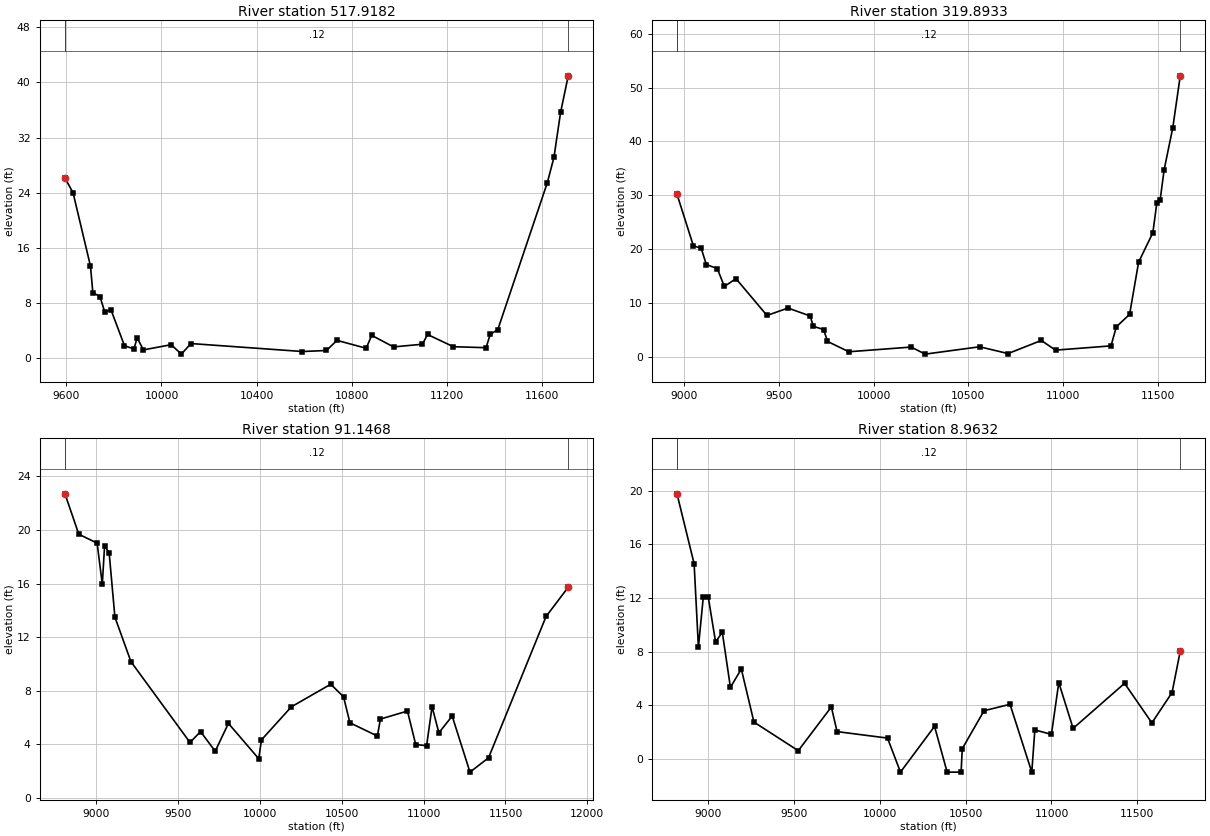
Type RM Length L Ch R = 1 ,517.9182,198.024900,198.024900,198.024900
XS GIS Cut Line= 6
1226418.17429388638602.896216393 1227452.4296906638765.204649657
1227618.67822063638815.9760048541227740.38392538638860.947207034
1228042.11069545638985.8680235591228454.20818859639130.470530972
#Sta/Elev= 30
9594.67326.125199628.78823.977919701.849  13.3349711.8129.4964939741.7018.902477
9761.6276.7013029788.1956.9710989844.6521.7792669884.5041.3027239897.7882.911517
9924.3561.16965810040.591.92310510083.760.55439710123.612.09133410591.870.933914
10692.961.08292510737.232.55289510859.861.40540210883.14 3.2791810974.671.602624
11096.121.99116911117.583.40720711226.14 1.6303711363.541.48977411380.993.457857
 11412.44.08285511620.7725.4527411648.51 29.119311676.46 35.662211708.5440.96621
#Mann= 3 , 0 , 0
9594.673    0.12       09594.673    0.12       011708.54    0.12       0
#XS Ineff= 2 , 0
       0                10281.15       0
Bank Sta=9594.673,11708.54
Exp/Cntr=0.3,0.1

Type RM Length L Ch R = 1 ,319.8933,228.746500,228.746500,228.746500
XS GIS Cut Line= 4
1225751.47263521638579.9433131071226325.86844283638738.908942521
1227152.48971581638957.2217402611228280.08591378639381.130085364
#Sta/Elev= 30
8962.14830.201369048.89920.582869089.74920.168439116.98217.128379174.85316.36516
9212.29813.051729273.57314.494789436.9737.6572119548.0999.0341359664.7117.560283
9681.6785.6340299735.9715.0445059756.3312.8327519868.8640.90698910197.461.779701
10272.120.46765210558.94 1.8344210709.110.57129510884.363.00911710959.841.208217
11252.382.00218111280.435.53893711350.537.87042111398.04 17.5706 11473.223.03487
11494.2328.6057411511.7629.1614211532.7934.7602711578.3542.5544311617.7552.20288
#Mann= 3 , 0 , 0
8962.148    0.12       08962.148    0.12       011617.75    0.12       0
#XS Ineff= 2 , 0
       09835.477        10228.38       0
Bank Sta=8962.148,11617.75
Exp/Cntr=0.3,0.1

Type RM Length L Ch R = 1 , 91.1468,82.183600,82.183600,82.183600
XS GIS Cut Line= 6
1225513.12811553638660.763546795 1226497.8085987639027.103187323
1227045.60426277639110.5119813081227420.39462489639293.742825016
1227878.47173411 639710.176560671228290.74113241639835.106681377
#Sta/Elev= 30
8809.83122.700248894.30419.681579006.32119.019149037.82515.938749051.82718.82445
9079.83218.286539114.83713.489039212.85210.162059573.4074.1269649637.8544.938196
 9727.433.4716939807.9435.5506659993.1962.91389910009.794.32155810192.326.787718
10432.938.47678410511.067.537783 10549.85.59855510717.784.60486210736.045.872589
10901.36 6.4737110951.663.97419811018.293.88356911051.616.79442911093.254.848029
11174.376.09939911283.041.91058911396.442.98070211747.7413.5366211883.1115.72409
#Mann= 3 , 0 , 0
8809.831    0.12       08809.831    0.12       011883.11    0.12       0
#XS Ineff= 2 , 0
       09948.746        10235.01       0
Bank Sta=8809.831,11883.11
Exp/Cntr=0.3,0.1

Type RM Length L Ch R = 1 ,  8.9632,0.000000,0.000000,0.000000
XS GIS Cut Line= 6
1225467.72136542638781.3948673461226253.31164324639052.662228465
1227190.81164324639239.2941728981227520.67275432639475.839311808
1227696.45400432 639794.849728451228008.95400432639974.971256256
#Sta/Elev= 30
8820.10919.774848919.89214.558568944.8648.3243578973.40312.088119001.94212.08061
 9044.758.7235549083.9919.4373419131.2075.325207 9194.586.6993979268.0772.735174
9526.1110.6005689718.5973.8652969752.0162.02499610045.761.54162110120.87  -0.999
10319.342.41727410392.61  -0.99910473.92  -0.99910480.78 0.7538710607.593.584453
10758.584.06353210885.38  -0.99910903.182.15322210999.691.81846911042.435.687213
11125.912.26578511425.395.62942511584.432.67689511701.824.94122511749.538.027989
#Mann= 3 , 0 , 0
8820.109    0.12       08820.109    0.12       011749.53    0.12       0
#XS Ineff= 2 , 0
       09978.881        10110.76       0
Bank Sta=8820.109,11749.53
Exp/Cntr=0.3,0.1